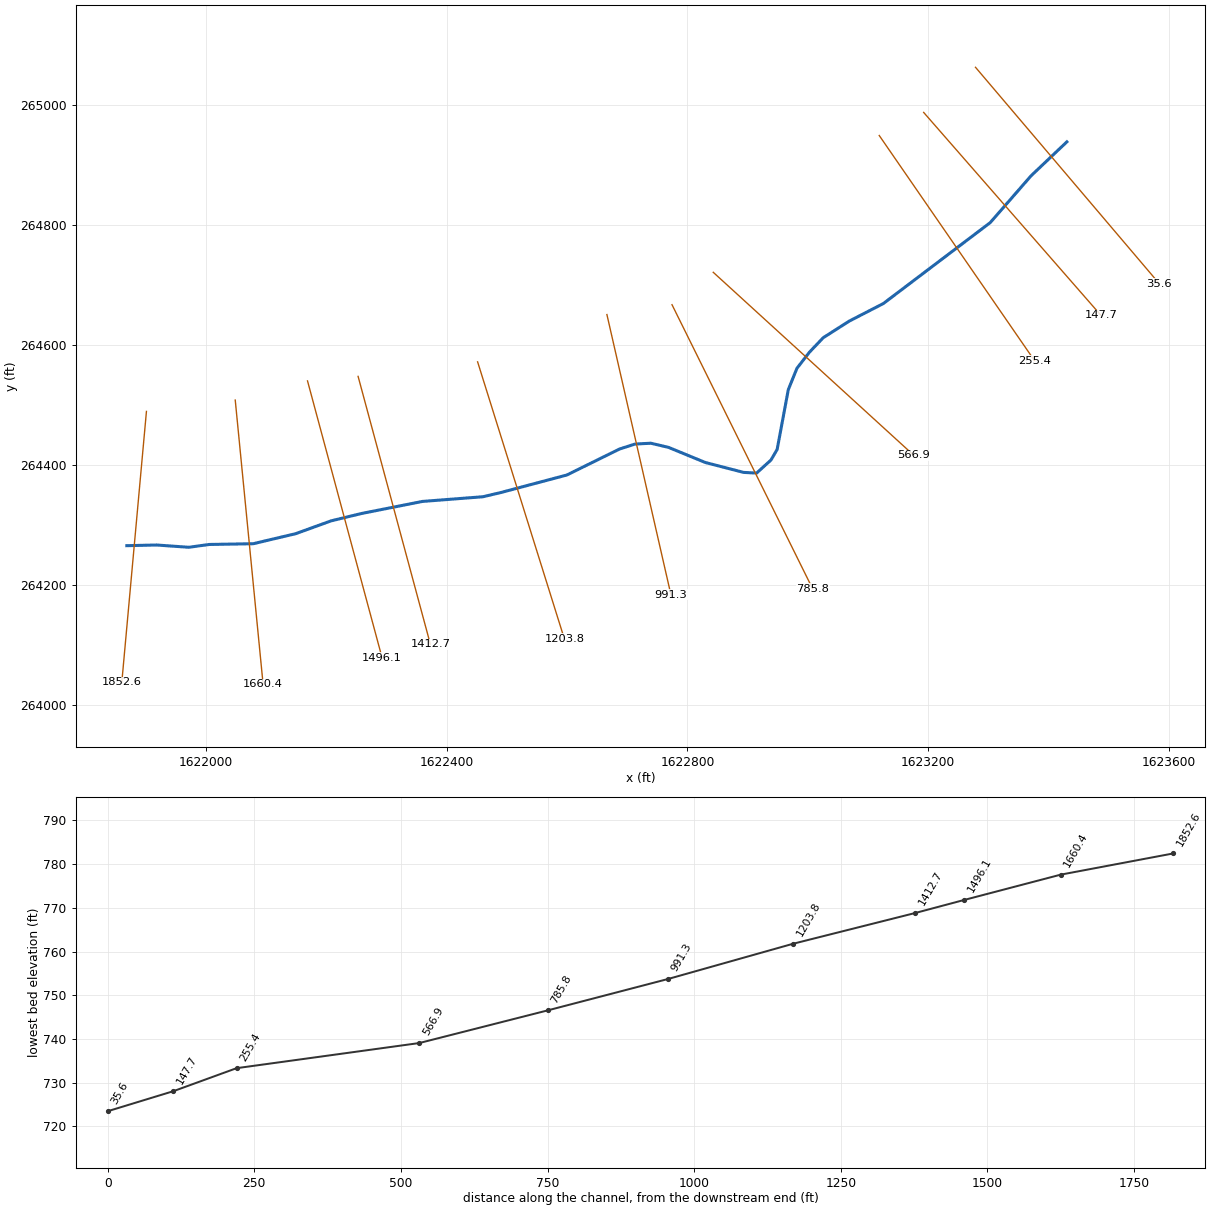
--- pgnrstcrk.prj (project) ---

Proj Title=pgnrstcrk
Current Plan=p01
Default Exp/Contr=0,0
English Units
Geom File=g01
Flow File=f01
Plan File=p01
BEGIN DESCRIPTION:
END DESCRIPTION:
DSS Export Rating Curves= 0
DSS Export Rating Curve Sorted= 0
DSS Export Volume Flow Curves= 0
DXF OffsetX= 0
DXF OffsetY= 0
DXF ScaleX= 0
DXF ScaleY= 0

--- pgnrstcrk.p01 (plan) ---

Plan Title=Approximate Study - 100yr
Program Version=4.00
Geom File=g01
Flow File=f01
Subcritical Flow
K Sum by GR= 0
Std Step Tol= 0.01
Critical Tol= 0.01
Num of Std Step Trials= 20
Max Error Tol= 0.3
Flow Tol Ratio= 0.001
Split Flow NTrial= 30
Split Flow Tol= 0.02
Split Flow Ratio= 0.02
Log Output Level= 0
Friction Slope Method= 1
Unsteady Friction Slope Method= 2
Unsteady Bridges Friction Slope Method= 1
Parabolic Critical Depth
Global Vel Dist= 0 , 0 , 0
Global Log Level= 0
CheckData=True
Encroach Param=-1 ,0,0, 0
Run HTab= 0
Run UNet= 0
Run PostProcess= 0
Run WQNet= 0
UNET Theta= 0
UNET Theta Warmup= 0
UNET ZTol= 0
UNET ZSATol= 0
UNET MxIter= 0
UNET MaxInSteps= 0
UNET DtIC= 0
UNET DtMin= 0
UNET MaxCRTS= 0
UNET WFStab= 0
UNET SFStab= 0
UNET WFX= 1
UNET SFX= 1
UNET DSS MLevel= 1
UNET DZMax Abort= 0
UNET Convert EG Bridges= 0
UNET Use Existing IB Tables= 0
UNET Froude Reduction=False
UNET Froude Limit= 0
UNET Froude Power= 0
UNET Time Slicing=0,0, 5
Write IC File= 0
Echo Input=False
Echo Output=False
Write Detailed= 0
Detailed Automatic Start=False, 0
WQ ULTIMATE=-1
WQ Max Comp Step=1HOUR
WQ Output Interval=15MIN
WQ Output Selected Increments= 0
WQ Output face flow=0
WQ Output face velocity=0
WQ Output face area=0
WQ Output face dispersion=0
WQ Output cell volume=0
WQ Output cell surface area=0
WQ Output cell continuity=0
WQ Output face conc=0
WQ Output face dconc_dx=0
WQ Output face courant=0
WQ Output face peclet=0
WQ Output face adv mass=0
WQ Output face disp mass=0
WQ Output cell mass=0
WQ Output cell source sink temp=0
WQ Output cell source sink nsm=0
WQ Output MaxMinRange=-1
WQ Daily Max Min Mean=-1
WQ Daily Range=0
WQ Daily Time=0
WQ Create Restart=0
WQ Fixed Restart=0
WQ System Summary=False
Sorting and Armoring Iterations= 10
XS Update Threshold= 0.02
Hydraulics Update Threshold= 0.02
Energy Slope Method= 1
Volume Change Method= 0
XS Weighting Method= 0
Number of US Weighted Cross Sections= 1
Number of DS Weighted Cross Sections= 1
Upstream XS Weight=0.25
Main XS Weight=0.5
Downstream XS Weight=0.25
Number of DS XS's Weighted with US Boundary= 1
Upstream Boundary Weight= 1
Weight of XSs Associated with US Boundary= 0
Number of US XS's Weighted with DS Boundary= 1
Downstream Boundary Weight= 0.5
Weight of XSs Associated with DS Boundary= 0.5
Sediment Output Level= 4
Mass or Volume Output= 0
Output Increment Type= 1
Profile and TS Output Increment= 10
XS Output Flag= 0
XS Output Increment= 10
Disregard all LS=0
Disregard all Conn=0
Disregard all Breaches=0
Disregard all Pumps=0

--- pgnrstcrk.f01 (steady flow) ---

Flow Title=USGS Regression Equation
Program Version=4.00
Number of Profiles= 1
Profile Names=P100yr
River Rch & RM=pgnrstcrk,Main            ,1852.6
     355
River Rch & RM=pgnrstcrk,Main            ,1496.1
     394
River Rch & RM=pgnrstcrk,Main            ,255.4
     422
Boundary for River Rch & Prof#=pgnrstcrk,Main            , 1
Up Type= 0
Dn Type= 3
Dn Slope=0.019079
DSS Import GetInterval= 0
DSS Import GetPeak= 0
DSS Import FillOption= 0

--- pgnrstcrk.g01 (geometry) ---

Geom Title=USGS 3m DEM
Program Version=4.00

River Reach=pgnrstcrk       ,Main
Reach XY= 30
     1621868.232      264265.672     1621917.612      264266.804
     1621971.147      264262.998     1622005.249      264267.686
     1622078.295      264268.939     1622148.777       264285.61
     1622207.729      264307.008     1622258.368      264319.296
     1622359.492      264339.357     1622459.875      264347.156
     1622489.545      264354.099     1622599.564      264383.386
     1622687.069      264426.638     1622712.975      264434.972
     1622739.274      264436.281      1622768.33      264429.435
     1622829.783      264404.163     1622893.241      264387.717
     1622914.854      264386.584      1622938.75      264408.314
     1622949.016      264426.007     1622967.512      264525.397
     1622981.841      264561.047     1623002.699      264587.944
     1623025.656      264612.067     1623068.781      264639.654
     1623125.555      264668.957     1623303.072      264803.659
     1623371.044      264881.718     1623430.495      264938.214

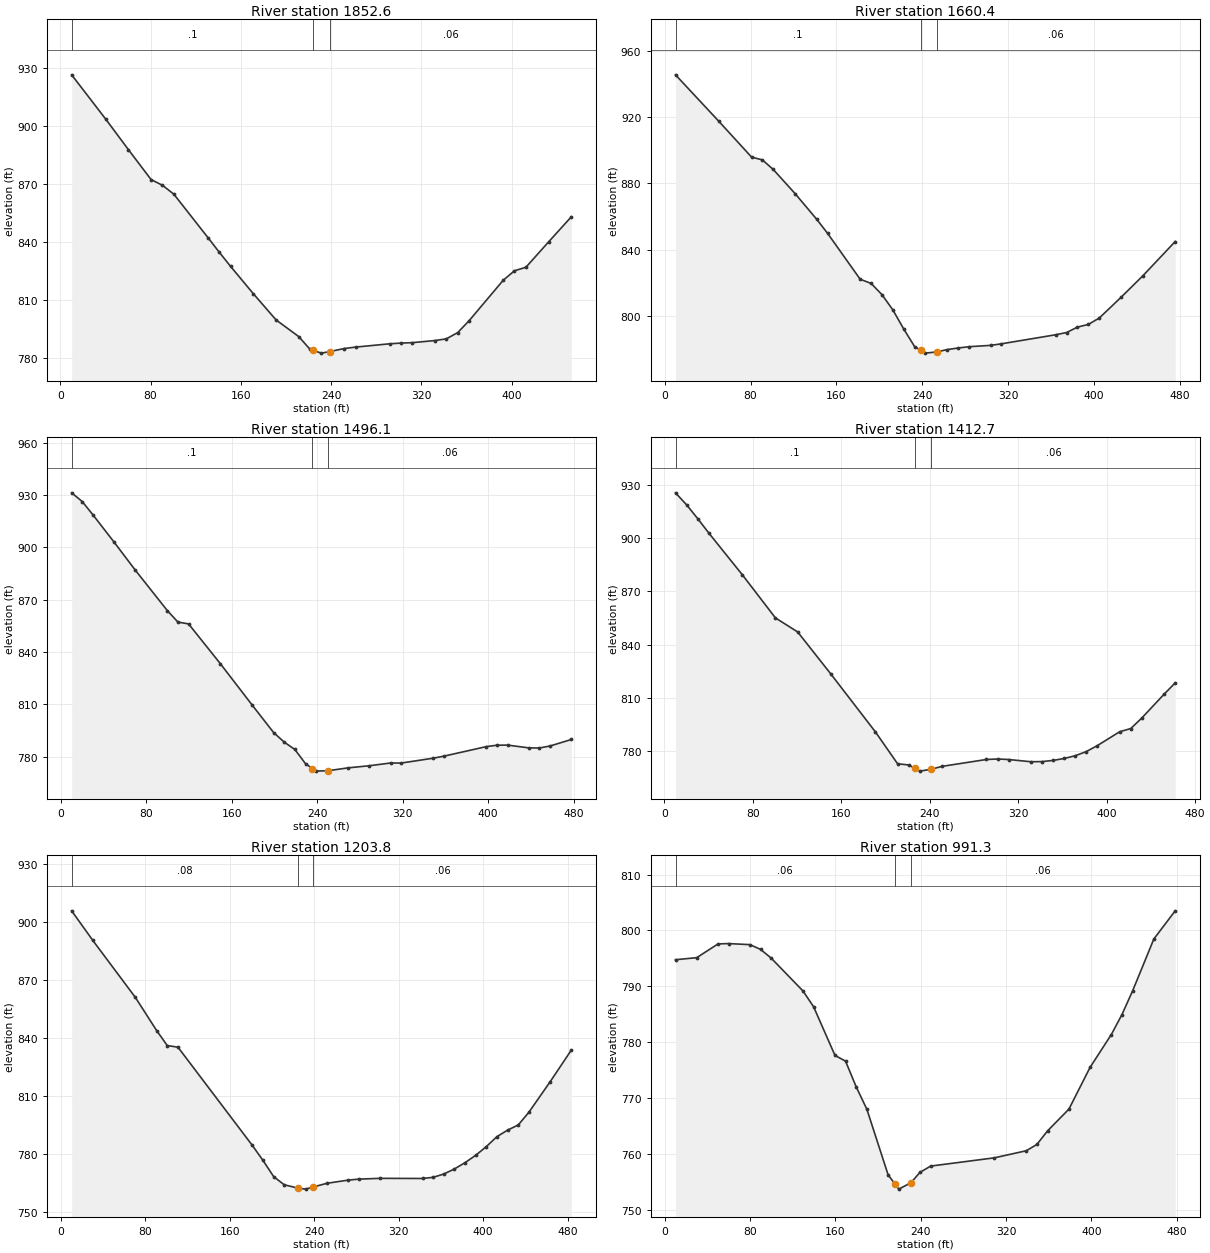
Type RM Length L Ch R = 1 ,1852.6  ,188,192.2,196.4
XS GIS Cut Line= 2
     1621900.839      264489.301      1621859.89      264038.182
#Sta/Elev= 30
    10.1  926.62    40.3  903.67    60.4  887.87    80.5  872.36    90.6  869.39
   100.7  864.78   130.9  842.29   140.9  834.75     151  827.36   171.1  813.25
   191.3  799.64   211.4     791   221.5  784.33     224  783.86   231.5  782.44
     239  783.26   251.7  784.82   261.7  785.56   291.9  787.27     302  787.64
     312  787.87   332.2  788.96   342.2  789.84   352.3  793.08   362.4  799.25
   392.6  820.18   402.6  825.12   412.7  826.91   432.8  840.05     453  853.08
#Mann= 3 , 0 , 0
    10.1      .1       0     224    .045       0     239     .06       0
Bank Sta=224,239
XS Rating Curve= 0 ,0
Exp/Cntr=0.3,0.1

Type RM Length L Ch R = 1 ,1660.4  ,160.5,164.3,168
XS GIS Cut Line= 2
       1622048.4      264508.175     1622094.727      264034.607
#Sta/Elev= 30
    10.1  945.39    50.6  917.29      81  895.77    91.1  894.09   101.2  888.32
   121.5  873.81   141.7  858.29   151.9  849.76   182.2  822.14   192.4  819.61
   202.5  812.85   212.6   803.7   222.7  792.24   232.9  781.56   238.5 779.356
     243  777.58   253.5 778.307   263.2   779.7   273.3  780.65   283.5  781.45
   303.7  782.25   313.8  783.19   364.5  788.66   374.6     790   384.7  793.27
   394.8  794.87     405  798.71   425.2  811.16   445.5  824.11   475.8  844.87
#Mann= 3 , 0 , 0
    10.1      .1       0   238.5    .045       0   253.5     .06       0
Bank Sta=238.5,253.5
XS Rating Curve= 0 ,0
Exp/Cntr=0.3,0.1

Type RM Length L Ch R = 1 ,1496.1  ,83.4,83.4,83.4
XS GIS Cut Line= 2
     1622168.521      264540.098     1622292.554      264078.579
#Sta/Elev= 30
      10  931.25    19.9  926.26    29.9  918.67    49.8  902.96    69.7  886.87
    99.6  863.77   109.5  857.21   119.5  856.14   149.3  833.31   179.2  809.52
   199.1  793.91   209.1  788.39     219  784.21     229  776.05   235.4 773.303
   238.9   771.8   250.4 772.057   268.8  773.67   288.7  774.88   308.6  776.46
   318.6  776.43   348.5   779.2   358.4  780.36   398.2  785.83   408.2  786.65
   418.2  786.71   438.1  785.12     448  785.06     458  786.21   477.9  789.93
#Mann= 3 , 0 , 0
      10      .1       0   235.4    .045       0   250.4     .06       0
Bank Sta=235.4,250.4
XS Rating Curve= 0 ,0
Exp/Cntr=0.3,0.1

Type RM Length L Ch R = 1 ,1412.7  ,208,208.9,209.8
XS GIS Cut Line= 2
     1622252.583      264547.639     1622372.691      264101.524
#Sta/Elev= 30
      10  925.55    20.1  918.76    30.1     911    40.2  902.85    70.3  879.52
   100.4  855.11   120.5  847.21   150.7  823.38   190.8  790.94   210.9  772.95
     221  772.29   226.5  770.38     231  768.82   241.5 769.894   251.1  771.51
   291.3  775.38   301.3  775.65   311.3  775.36   331.4  774.11   341.5  774.18
   351.5  774.85   361.6  775.94   371.6  777.49   381.7  779.86   391.7  783.23
   411.8  791.01   421.8   792.8   431.9   798.8     452  812.17     462  818.52
#Mann= 3 , 0 , 0
      10      .1       0   226.5    .045       0   241.5     .06       0
Bank Sta=226.5,241.5
XS Rating Curve= 0 ,0
Exp/Cntr=0.3,0.1

Type RM Length L Ch R = 1 ,1203.8  ,214.3,212.6,210.8
XS GIS Cut Line= 2
     1622451.202      264571.827     1622595.426      264110.308
#Sta/Elev= 30
    10.1  905.55    30.2  890.22    70.5  860.79    90.7  843.62   100.7  835.93
   110.8  835.11   181.3  784.33   191.4  776.56   201.5  768.21   211.5     764
   224.2  762.33   231.7  761.76   239.2   762.9   251.8  764.76     272  766.41
   282.1  766.93   302.2  767.33   342.5  767.26   352.6  767.86   362.6  769.56
   372.7  772.17   382.8  775.44   392.9  779.24   402.9   783.7     413  788.87
   423.1  792.24   433.2  794.91   443.2  801.43   463.4  817.23   483.5  833.61
#Mann= 3 , 0 , 0
    10.1     .08       0   224.2    .045       0   239.2     .06       0
Bank Sta=224.2,239.2
XS Rating Curve= 0 ,0
Exp/Cntr=0.3,0.1

Type RM Length L Ch R = 1 ,991.3   ,199.1,205.4,211.4
XS GIS Cut Line= 2
     1622666.097      264650.588     1622772.478      264183.884
#Sta/Elev= 30
      10  794.76    29.9  795.13    49.9  797.59    59.8  797.65    79.8  797.46
    89.8  796.61    99.7  795.06   129.6  789.17   139.6  786.32   159.6  777.64
   169.5  776.62   179.5  772.01   189.5  768.01   209.4  756.29   215.9 754.621
   219.4  753.72   230.9  754.87   239.3  756.72   249.3  757.84   309.1  759.32
   339.1  760.59     349  761.72     359  764.15     379  768.03   398.9  775.52
   418.8  781.38   428.8  784.96   438.8  789.21   458.7  798.48   478.7  803.51
#Mann= 3 , 0 , 0
      10     .06       0   215.9    .045       0   230.9     .06       0
Bank Sta=215.9,230.9
XS Rating Curve= 0 ,0
Exp/Cntr=0.3,0.1

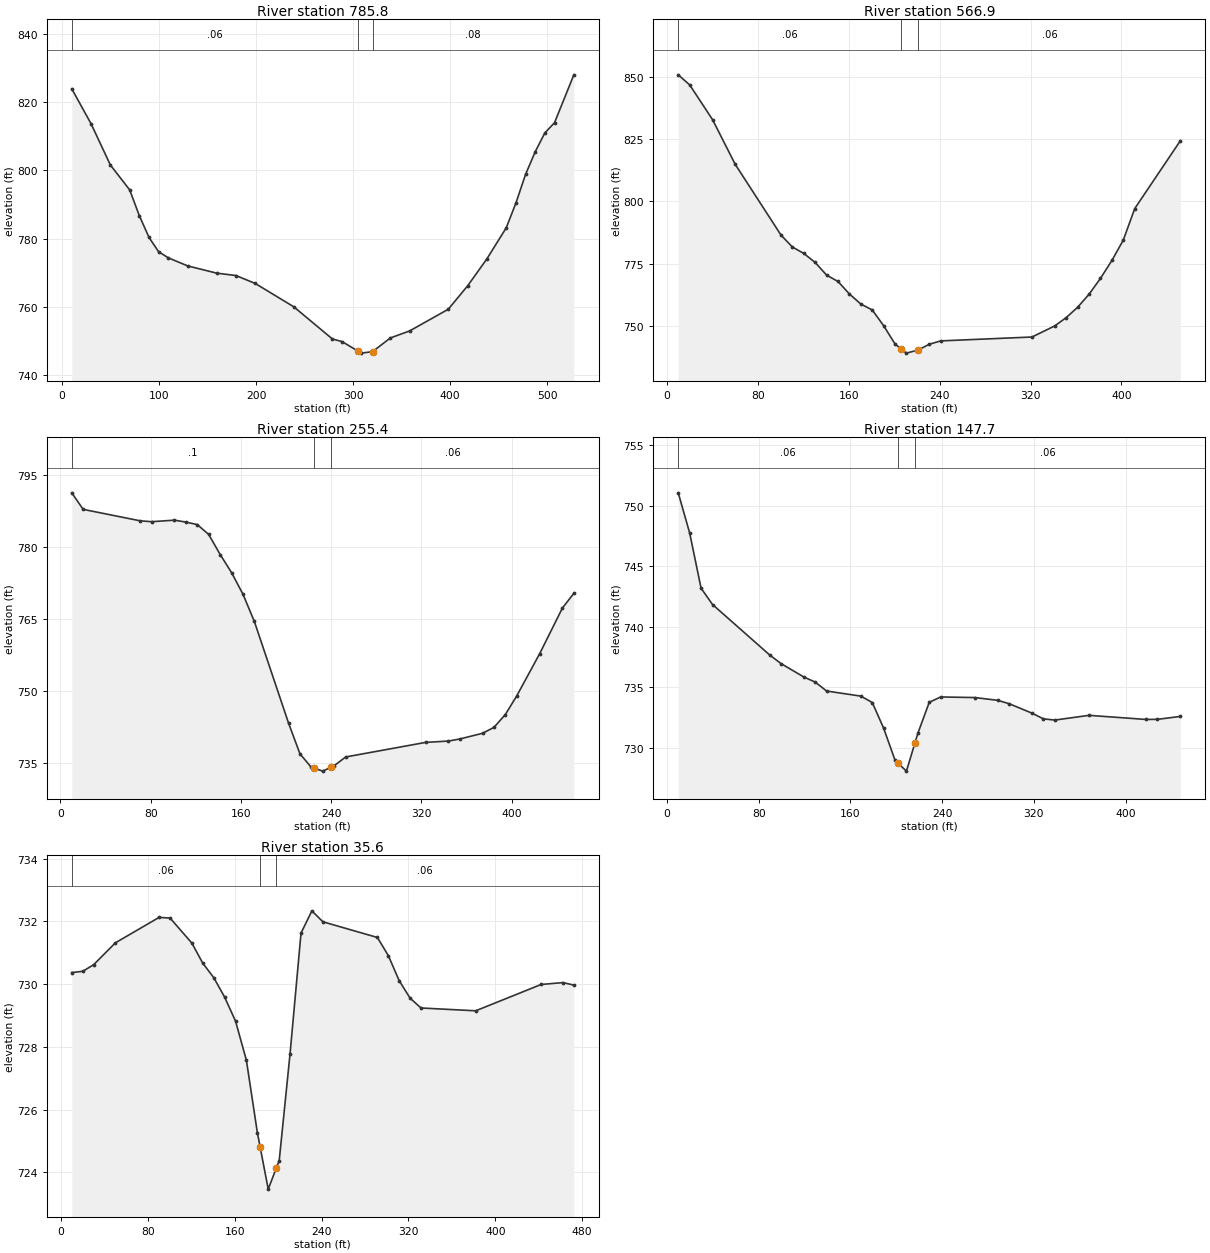
Type RM Length L Ch R = 1 ,785.8   ,211.1,218.9,227.1
XS GIS Cut Line= 2
     1622774.265      264667.016     1623007.909      264193.958
#Sta/Elev= 30
      10  823.91    29.9  813.67    49.8  801.61    69.7  794.32    79.6   786.8
    89.6  780.42    99.5  776.22   109.5  774.43   129.4  772.07   159.3  769.95
   179.2  769.25   199.1  766.93   238.9  760.09   278.7  750.67   288.7   749.9
   305.1 747.113   308.6  746.53   320.1 746.969   338.5  750.98   358.4  753.04
   398.2  759.39   418.1  766.23     438  774.14   457.9  783.21   467.9  790.48
   477.8  798.83   487.8  805.49   497.7  810.99   507.7  813.99   527.6     828
#Mann= 3 , 0 , 0
      10     .06       0   305.1    .045       0   320.1     .08       0
Bank Sta=305.1,320.1
XS Rating Curve= 0 ,0
Exp/Cntr=0.3,0.1

Type RM Length L Ch R = 1 ,566.9   ,316.7,311.5,306.4
XS GIS Cut Line= 2
     1622842.826      264720.937      1623176.24      264416.029
#Sta/Elev= 30
      10  850.75    20.1   846.7    40.2  832.76    60.2  814.78   100.4  786.46
   110.4  781.66   120.5  779.07   130.5  775.44   140.6  770.35   150.6  767.82
   160.6  762.81   170.7  758.75   180.7   756.4   190.8  750.03   200.8  742.71
   206.3 740.704   210.8  739.06   221.3 740.326   230.9  742.63     241  743.97
   321.3  745.53   341.4     750   351.4  753.32   361.4  757.44   371.5   762.7
   381.5  769.03   391.6  776.25   401.6   784.4   411.7  797.07   451.8  824.27
#Mann= 3 , 0 , 0
      10     .06       0   206.3    .045       0   221.3     .06       0
Bank Sta=206.3,221.3
XS Rating Curve= 0 ,0
Exp/Cntr=0.3,0.1

Type RM Length L Ch R = 1 ,255.4   ,105.1,107.7,110.2
XS GIS Cut Line= 2
     1623118.654      264948.789     1623376.627      264573.987
#Sta/Elev= 30
    10.1  791.34    20.2  787.89    70.8   785.5    80.9  785.32   101.1  785.64
   111.2  785.24   121.3  784.72   131.4  782.67   141.6  778.48   151.7   774.7
   161.8   770.2   171.9  764.51   202.2  743.32   212.3  736.92   222.4  734.09
   225.1  733.89   232.6  733.31   240.1  734.16   242.7  734.45   252.8  736.26
   323.6   739.3   343.8  739.58   353.9  740.01   374.1   741.2   384.2  742.43
   394.3  745.11   404.4     749   424.7  757.79   444.9  767.33     455  770.39
#Mann= 3 , 0 , 0
    10.1      .1       0   225.1    .045       0   240.1     .06       0
Bank Sta=225.1,240.1
XS Rating Curve= 0 ,0
Exp/Cntr=0.3,0.1

Type RM Length L Ch R = 1 ,147.7   ,112.3,112.1,111.8
XS GIS Cut Line= 2
     1623192.517      264987.195     1623486.735      264649.709
#Sta/Elev= 29
     9.9  751.05    19.9  747.72    29.8  743.17    39.8  741.82    89.5  737.66
    99.5  736.94   119.4  735.83   129.3  735.41   139.3  734.67   169.1  734.25
   179.1  733.72     189   731.6     199  728.94   201.4  728.72   208.9  728.05
   216.4  730.41   218.9  731.19   228.8  733.74   238.8  734.18   268.6  734.13
   288.5   733.9   298.5  733.62   318.4  732.84   328.3  732.37   338.3  732.27
   368.1  732.66   417.9  732.32   427.8  732.33   447.7  732.57
#Mann= 3 , 0 , 0
     9.9     .06       0   201.4    .045       0   216.4     .06       0
Bank Sta=201.4,216.4
XS Rating Curve= 0 ,0
Exp/Cntr=0.3,0.1

Type RM Length L Ch R = 1 ,35.6    ,34.7,35.6,36.5
XS GIS Cut Line= 2
     1623278.646      265062.386     1623584.062      264702.063
#Sta/Elev= 30
      10  730.37    20.1  730.41    30.1  730.62    50.2  731.32    90.4  732.13
   100.5  732.11   120.6  731.31   130.6  730.67   140.7  730.21   150.7  729.59
   160.8  728.82   170.8  727.57   180.9  725.26   183.4  724.81   190.9  723.46
   198.4  724.14     201  724.37     211  727.78   221.1  731.63   231.1  732.34
   241.2  731.99   291.4  731.49   301.5  730.91   311.5  730.11   321.6  729.55
   331.6  729.24   381.9  729.15   442.2  729.99   462.3  730.05   472.3  729.97
#Mann= 3 , 0 , 0
      10     .06       0   183.4    .045       0   198.4     .06       0
Bank Sta=183.4,198.4
XS Rating Curve= 0 ,0
Exp/Cntr=0.3,0.1

Chan Stop Cuts=-1
Use User Specified Reach Order=0